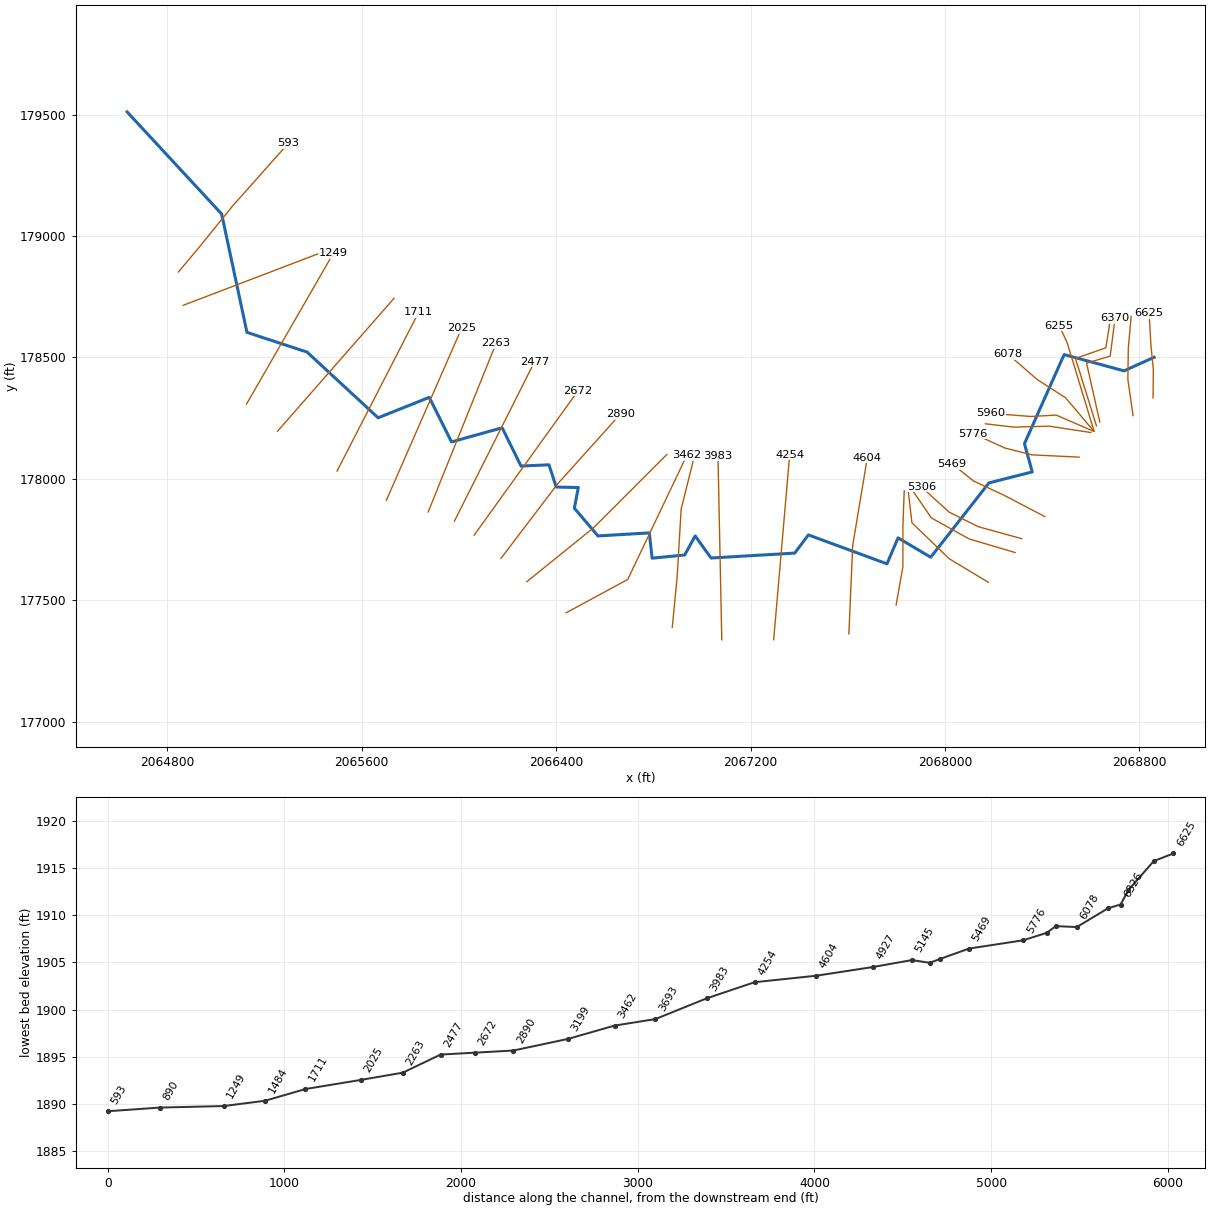
--- LICKRN.prj (project) ---

Proj Title=LICKRN
Current Plan=p01
Default Exp/Contr=0,0
English Units
Geom File=g01
Flow File=f01
Plan File=p01
Background Map Layer=Inundation Boundary (01pct Value_0)
Background Map Layer=Inundation Boundary (01pct Value_0)
BEGIN DESCRIPTION:
Stream Name: Lick Run
Flood Zone: Approximate
Monroe County, West Virginia
HEC-RAS Version: 5.0.7
Vertical Datum: NAVD88
Projection: NAD 1983 StatePlane West Virginia S FIPS 4702 (US Feet)
LiDAR: 2016, 1-meter
Land Use: 2016 NLCD
Hydrology Method:
Regression.
Model Notes:
END DESCRIPTION:
DSS Export Rating Curves= 0
DSS Export Rating Curve Sorted= 0
DSS Export Volume Flow Curves= 0
DXF OffsetX= 0
DXF OffsetY= 0
DXF ScaleX= 0
DXF ScaleY= 0

--- LICKRN.p01 (plan) ---

Plan Title=Floodplain
Program Version=5.07
Short Identifier=Floodplain
Geom File=g01
Flow File=f01
Subcritical Flow
K Sum by GR= 0
Std Step Tol= 0.01
Critical Tol= 0.01
Num of Std Step Trials= 20
Max Error Tol= 0.3
Flow Tol Ratio= 0.001
Split Flow NTrial= 30
Split Flow Tol= 0.02
Split Flow Ratio= 0.02
Log Output Level= 0
Friction Slope Method= 1
Unsteady Friction Slope Method= 2
Unsteady Bridges Friction Slope Method= 1
Parabolic Critical Depth
Global Vel Dist= 0 , 0 , 0
Global Log Level= 0
CheckData=True
Encroach Param=-1 ,0,0, 0
Mapping Interval=1HOUR
Computation Time Step Use Courant=        0
Computation Time Step Use Time Series=    0
Computation Time Step Count To Double=0
Computation Time Step Max Doubling=0
Computation Time Step Max Halving=0
Computation Time Step Residence Courant=0
Run HTab= 0
Run UNet= 0
Run Sediment= 0
Run PostProcess= 0
Run WQNet= 0
Run RASMapper=-1
UNET Theta= 0
UNET Theta Warmup= 0
UNET ZTol= 0
UNET ZSATol= 0
UNET MxIter= 0
UNET Max Iter WO Improvement= 0
UNET MaxInSteps= 0
UNET DtIC= 0
UNET DtMin= 0
UNET MaxCRTS= 0
UNET WFStab= 0
UNET SFStab= 0
UNET WFX= 1
UNET SFX= 1
UNET 1D Methodology=Finite Difference
UNET DSS MLevel= 1
UNET Pardiso=0
UNET DZMax Abort= 0
UNET Use Existing IB Tables= 0
UNET Froude Reduction=False
UNET Froude Limit= 0
UNET Froude Power= 0
UNET D1 Cores= 0
UNET D2 Coriolis=0
UNET D2 Cores= 0
UNET D2 Theta= 1
UNET D2 Theta Warmup= 1
UNET D2 Z Tol= 0.01
UNET D2 Volume Tol= 0.01
UNET D2 Max Iterations= 20
UNET D2 Equation= 0
UNET D2 RampUpFraction=0.1
UNET D2 TimeSlices= 1
UNET D2 BCVolumeCheck=0
UNET D1D2 MaxIter= 0
UNET D1D2 ZTol=0.01
UNET D1D2 QTol=0.1
UNET D1D2 MinQTol=1
Write IC File= 0
Write IC File at Fixed DateTime=0
Write IC File at Sim End=0
Echo Input=False
Echo Parameters=False
Echo Output=False
Write Detailed= 0
HDF Write Warmup=0
HDF Write Time Slices=0
HDF Flush=0
HDF Face Node Velocities=0
HDF Compression= 1
HDF Chunk Size= 1
HDF Spatial Parts= 1
HDF Use Max Rows=0
HDF Fixed Rows= 1
Calibration Method= 0
Calibration Iterations= 20
Calibration Max Change=0.05
Calibration Tolerance=0.2
Calibration Maximum=1.5
Calibration Minimum=0.5
Calibration Optimization Method= 1
WQ AD Non Conservative
WQ ULTIMATE=-1
WQ Max Comp Step=1HOUR
WQ Output Interval=15MIN
WQ Output Selected Increments= 0
WQ Output face flow=0
WQ Output face velocity=0
WQ Output face area=0
WQ Output face dispersion=0
WQ Output cell volume=0
WQ Output cell surface area=0
WQ Output cell continuity=0
WQ Output cumulative cell continuity=0
WQ Output face conc=0
WQ Output face dconc_dx=0
WQ Output face courant=0
WQ Output face peclet=0
WQ Output face adv mass=0
WQ Output face disp mass=0
WQ Output cell mass=0
WQ Output cell source sink temp=0
WQ Output nsm pathways=0
WQ Output nsm derived pathways=0
WQ Output MaxMinRange=-1
WQ Daily Max Min Mean=-1
WQ Daily Range=0
WQ Daily Time=0
WQ Create Restart=0
WQ Fixed Restart=0
WQ System Summary=0
WQ Write To DSS=0
WQ Use Fixed Temperature=0
Sorting and Armoring Iterations= 10
XS Update Threshold= 0.02
Bed Roughness Predictor= 0
Hydraulics Update Threshold= 0.02
Energy Slope Method= 1
Volume Change Method= 1
Sediment Retention Method= 0
XS Weighting Method= 0
Number of US Weighted Cross Sections= 1
Number of DS Weighted Cross Sections= 1
Upstream XS Weight=0
Main XS Weight=1
Downstream XS Weight=0
Number of DS XS's Weighted with US Boundary= 1
Upstream Boundary Weight= 1
Weight of XSs Associated with US Boundary= 0
Number of US XS's Weighted with DS Boundary= 1
Downstream Boundary Weight= 0.5
Weight of XSs Associated with DS Boundary= 0.5
Percentile Method= 0
Sediment Output Level= 3
Mass or Volume Output= 0
Output Increment Type= 1
Profile and TS Output Increment= 1
XS Output Flag= 0
XS Output Increment= 10
Write Gradation File= 0
Read Gradation Hotstart= 0
Write HDF5 File= 1
Write Binary Output= 1
Write DSS Sediment File= 0
SV Curve= 0
Specific Gage Flag= 0

--- LICKRN.f01 (steady flow) ---

Flow Title=Flow
Program Version=5.07
Number of Profiles= 6
Profile Names=01pct,10pct,04pct,02pct,0_2pct,01plus
River Rch & RM=LICKRN,Main            ,6625
     518     272     363     438     724     766
River Rch & RM=LICKRN,Main            ,4604
     578     306     406     490     808     855
Boundary for River Rch & Prof#=LICKRN,Main            , 1
Up Type= 0
Dn Type= 3
Dn Slope=0.00513
Boundary for River Rch & Prof#=LICKRN,Main            , 2
Up Type= 0
Dn Type= 3
Dn Slope=0.00513
Boundary for River Rch & Prof#=LICKRN,Main            , 3
Up Type= 0
Dn Type= 3
Dn Slope=0.00513
Boundary for River Rch & Prof#=LICKRN,Main            , 4
Up Type= 0
Dn Type= 3
Dn Slope=0.00513
Boundary for River Rch & Prof#=LICKRN,Main            , 5
Up Type= 0
Dn Type= 3
Dn Slope=0.00513
Boundary for River Rch & Prof#=LICKRN,Main            , 6
Up Type= 0
Dn Type= 3
Dn Slope=0.00513
DSS Import GetInterval= 0
DSS Import GetPeak= 0
DSS Import FillOption= 0

--- LICKRN.g01 (geometry) ---

Geom Title=Geometry
Program Version=5.07

River Reach=LICKRN          ,Main
Reach XY= 30
2068860.64663881178500.7365658132068736.98054755178444.893173561
2068490.50302213178511.9520945552068327.22283688178145.187080055
2068359.34088288178029.1102124752068181.01315555177983.813058972
2067941.41389722177677.9052062332067806.82492755177757.577619061
2067761.39949347177650.6267174782067437.95722698177769.810206145
2067381.70701139177694.8100280612067037.26314647177674.670960724
2066971.98506181177765.6432197242066928.93002981 177687.17093572
2066794.90208264177673.977064475 2066783.2570928 177778.00507164
2066571.98520564177765.6432197242066474.76295914 177879.53209956
2066491.10019681177964.7750393152066400.07511638177966.743211225
2066370.33108139178058.2650098062066255.31917231178053.142972812
2066177.62313347 178210.609193312065969.20721172178152.449204639
2065877.54105647178335.7821713092065667.12415446 178251.75412415
2065374.68412255 178522.295249732065127.32405297178603.273106143
2065023.15726656179090.4699663972064634.18691589179510.640057817

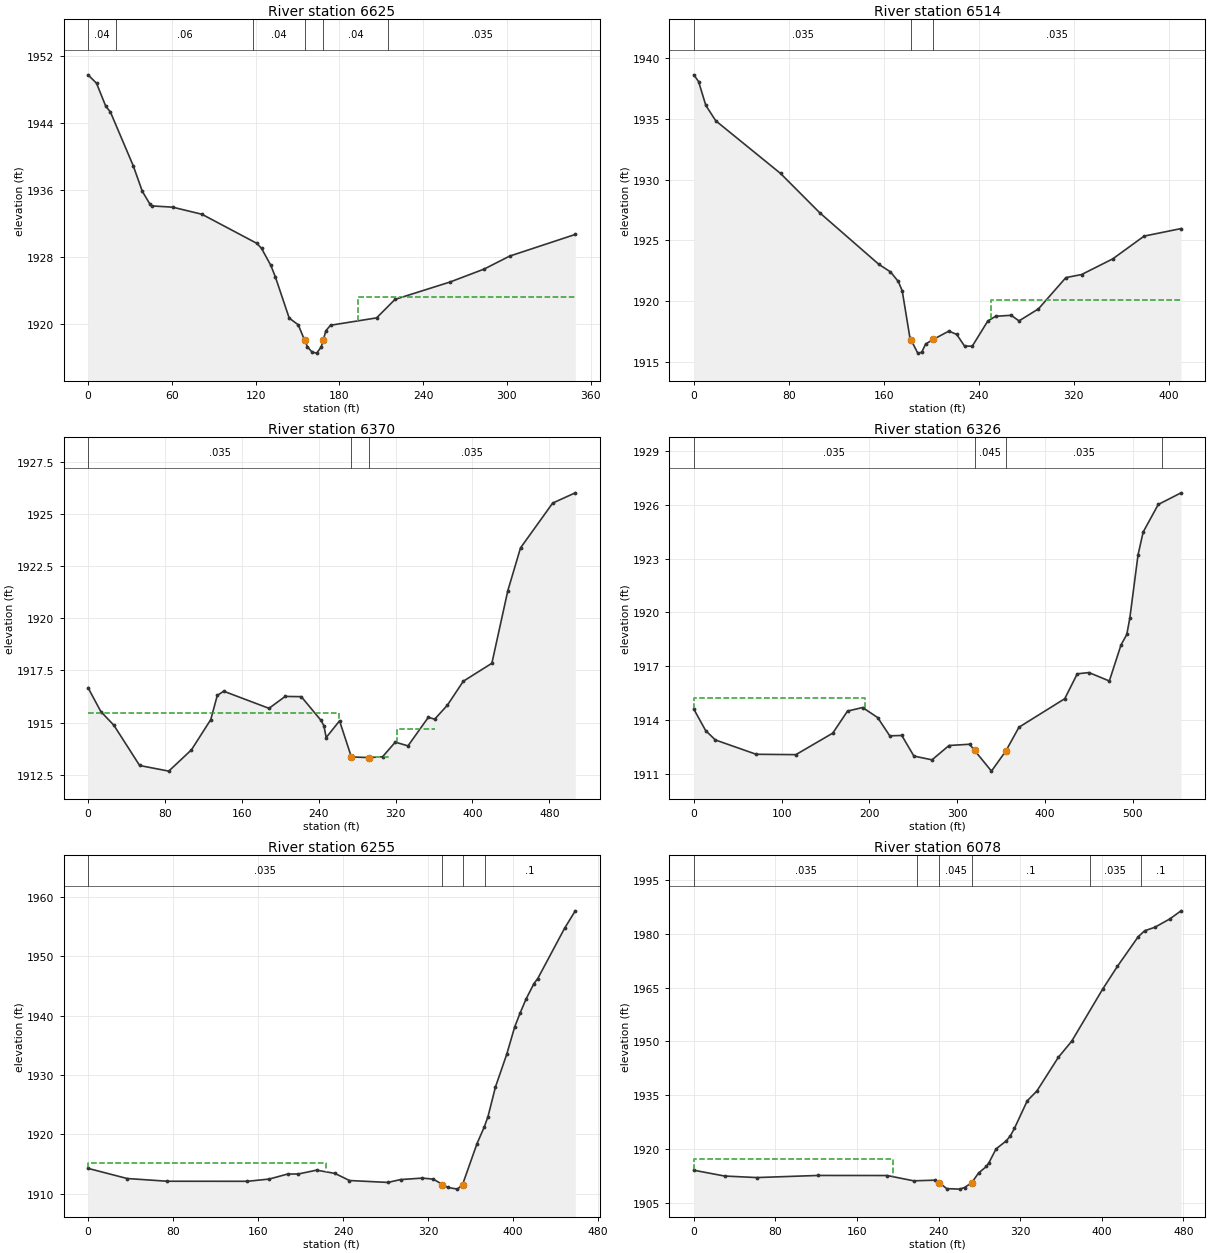
Type RM Length L Ch R = 1 ,6625    ,111.7,111.8,107.5
XS GIS Cut Line= 4
2068856.58251338178333.666769761 2068857.5527446178452.034978403
2068847.85043242178548.0878690232068840.08858267178681.979777159
#Sta/Elev= 30
       0 1949.81     6.1  1948.8    12.7 1946.06      16 1945.38    32.4 1938.94
    38.9 1935.89    44.1 1934.43    45.5 1934.15    60.6    1934    81.6 1933.15
     121 1929.67   124.3 1929.07   130.9 1927.06   134.2 1925.67   144.1 1920.75
   150.6 1919.94  155.151918.101   157.2 1917.31   160.5 1916.68   163.8 1916.56
   167.1 1917.31  168.451918.099   170.4 1919.24   173.7 1919.89   206.7 1920.77
   219.9 1922.98   259.4 1925.06   283.7  1926.6     302 1928.15349.0305 1930.74
#Mann= 6 ,-1 , 0
       0     .04       0      20     .06       0  118.37     .04       0
  155.15    .045       0  168.45     .04       0  214.91    .035       0
#XS Ineff= 2 , 0
                          193.05         1923.24
Permanent Ineff=
       F       F
Bank Sta=155.15,168.45
XS Rating Curve= 0 ,0
Exp/Cntr(USF)=0,0
Exp/Cntr=0.3,0.1

Type RM Length L Ch R = 1 ,6514    ,162,143.4,126.8
XS GIS Cut Line= 4
2068774.11285982178260.8994283822068752.76777301178409.344804795
2068754.70823545178539.3557880582068766.35101007178669.366771321
#Sta/Elev= 30
       0 1938.62       4 1938.07    10.1 1936.11    18.5 1934.84    73.1 1930.51
   106.2 1927.27   155.9 1923.04   165.7 1922.42   172.3 1921.63   175.6 1920.86
   182.1 1916.99  183.071916.818   188.7 1915.74     192 1915.81   195.3 1916.49
   201.8 1916.87   214.9 1917.55   221.5 1917.28   228.1 1916.32   234.6 1916.31
   247.7 1918.38   254.3 1918.77   267.4 1918.85     274 1918.39   290.4 1919.38
   313.5 1921.95   326.7  1922.2     353 1923.49   379.4 1925.36410.5289 1925.98
#Mann= 3 ,-1 , 0
       0    .035       0  183.07    .045       0   201.8    .035       0
#XS Ineff= 2 , 0
                          250.72          1920.1
Permanent Ineff=
       F       F
Bank Sta=183.07,201.8
XS Rating Curve= 0 ,0
Exp/Cntr(USF)=0,0
Exp/Cntr=0.5,0.3

Type RM Length L Ch R = 1 ,6370    ,48.8,44.1,40.2
XS GIS Cut Line= 4
2068637.23187249178234.8477620222068582.80524843178476.616555186
 2068680.2002599178505.8350586252068700.15990503178662.029991955
#Sta/Elev= 30
       0 1916.67    13.4 1915.52    26.9 1914.87    53.7 1912.94      84 1912.67
   107.6 1913.69   127.7 1915.14   134.5  1916.3   141.2  1916.5   188.3 1915.68
   205.1 1916.25   221.9 1916.24   242.1 1915.12   245.4 1914.85   247.8 1914.28
   261.7 1915.08     274 1913.35   292.3 1913.32   306.5 1913.36   319.7 1914.06
   332.9 1913.88   354.1 1915.25   360.7 1915.16   373.9 1915.83   390.5 1916.98
   420.2 1917.84   436.8 1921.32     450 1923.37   483.5 1925.52506.9677 1926.01
#Mann= 3 ,-1 , 0
       0    .035       0     274    .045       0   292.3    .035       0
#XS Ineff= 4 ,-1
       0  261.32 1915.48  264.19   271.3 1913.42  298.28  313.75 1913.35
  321.49  361.03  1914.7
Permanent Ineff=
       F       F       F       F
Bank Sta=274,292.3
XS Rating Curve= 0 ,0
Exp/Cntr(USF)=0,0
Exp/Cntr=0.5,0.3

Type RM Length L Ch R = 1 ,6326    ,39.7,71.3,98.2
XS GIS Cut Line= 4
2068623.51163878178218.6343251552068537.16106035178496.120453612
2068662.32088752178539.780858439 2068682.6957431178669.791841702
#Sta/Elev= 30
       0  1914.6    13.5  1913.4    24.5 1912.88      71 1912.08   116.2 1912.06
   158.2 1913.26     175 1914.49   192.2 1914.69   209.3 1914.13   223.1 1913.11
   236.8 1913.13   250.6 1911.98   271.2 1911.77   290.6 1912.57     314 1912.64
   319.6  1912.3   338.9 1911.14  355.341912.269   370.2 1913.59   422.3 1915.18
   436.6 1916.57   449.9 1916.64   473.1 1916.17   486.4 1918.18     493 1918.77
   496.4 1919.67   505.8 1923.21   511.6 1924.48   528.8 1926.02554.7657 1926.67
#Mann= 4 ,-1 , 0
       0    .035       0   319.6    .045       0  355.34    .035       0
  533.17      .1       0
#XS Ineff= 3 ,-1
       0  195.13 1915.22  301.72  312.03 1912.22  360.17  375.64 1912.22
Permanent Ineff=
       F       F       F
Bank Sta=319.6,355.34
XS Rating Curve= 0 ,0
Exp/Cntr(USF)=0,0
Exp/Cntr=0.5,0.3

Type RM Length L Ch R = 1 ,6255    ,166.5,176.4,185.1
XS GIS Cut Line= 4
 2068613.8093266178196.3190071322068522.60759207178496.120453612
 2068503.2029677178560.1557140252068470.21510628178630.982592967
#Sta/Elev= 30
       0 1914.24    36.8 1912.53    74.5 1912.07     150 1912.06   170.5 1912.44
   187.7 1913.28     198  1913.3   215.1 1913.94   232.3 1913.39     246 1912.19
   282.2 1911.87     294 1912.35   314.6  1912.6   324.9 1912.42  333.491911.512
   338.6 1911.02   347.6 1910.74  352.381911.512     366 1918.43   372.8 1921.22
   376.3 1922.97   383.3 1927.95   393.9 1933.46   401.4 1938.07   406.4 1940.38
   412.2 1942.82   419.5 1945.38   423.1 1946.24   448.4 1954.73458.4097 1957.66
#Mann= 4 ,-1 , 0
       0    .035       0  333.49    .045       0  352.38    .035       0
  373.37      .1       0
#XS Ineff= 2 , 0
           223.5  1915.1
Permanent Ineff=
       F       F
Bank Sta=333.49,352.38
XS Rating Curve= 0 ,0
Exp/Cntr(USF)=0,0
Exp/Cntr=0.3,0.1

Type RM Length L Ch R = 1 ,6078    ,107.2,118.6,131.6
XS GIS Cut Line= 4
2068612.01002581178197.5420767332068496.51064213178334.234369656
2068379.50075719178409.3302659592068258.99803987178514.115237544
#Sta/Elev= 30
       0 1914.03    30.1 1912.41    61.7 1911.98   121.8 1912.57   189.5 1912.55
   215.5 1911.07   236.3 1911.25  240.681910.522     248 1908.89   260.7 1908.75
   265.4  1909.2   272.41910.523   279.2 1913.26   286.8 1915.07   289.2 1916.05
   296.3 1919.98   306.5 1922.27   310.4 1923.67   314.3  1925.7   326.9 1933.42
   336.3 1936.14   357.3 1945.53   370.4 1950.03   400.8 1964.59   415.3 1970.97
   435.6 1979.21     442  1980.9     452 1981.88   466.5 1984.18477.6796 1986.47
#Mann= 6 ,-1 , 0
       0    .035       0  218.95      .1       0  240.68    .045       0
   272.4      .1       0  387.99    .035       0  437.99      .1       0
#XS Ineff= 2 , 0
          195.56 1917.06
Permanent Ineff=
       F       F
Bank Sta=240.68,272.4
XS Rating Curve= 0 ,0
Exp/Cntr(USF)=0,0
Exp/Cntr=0.5,0.3

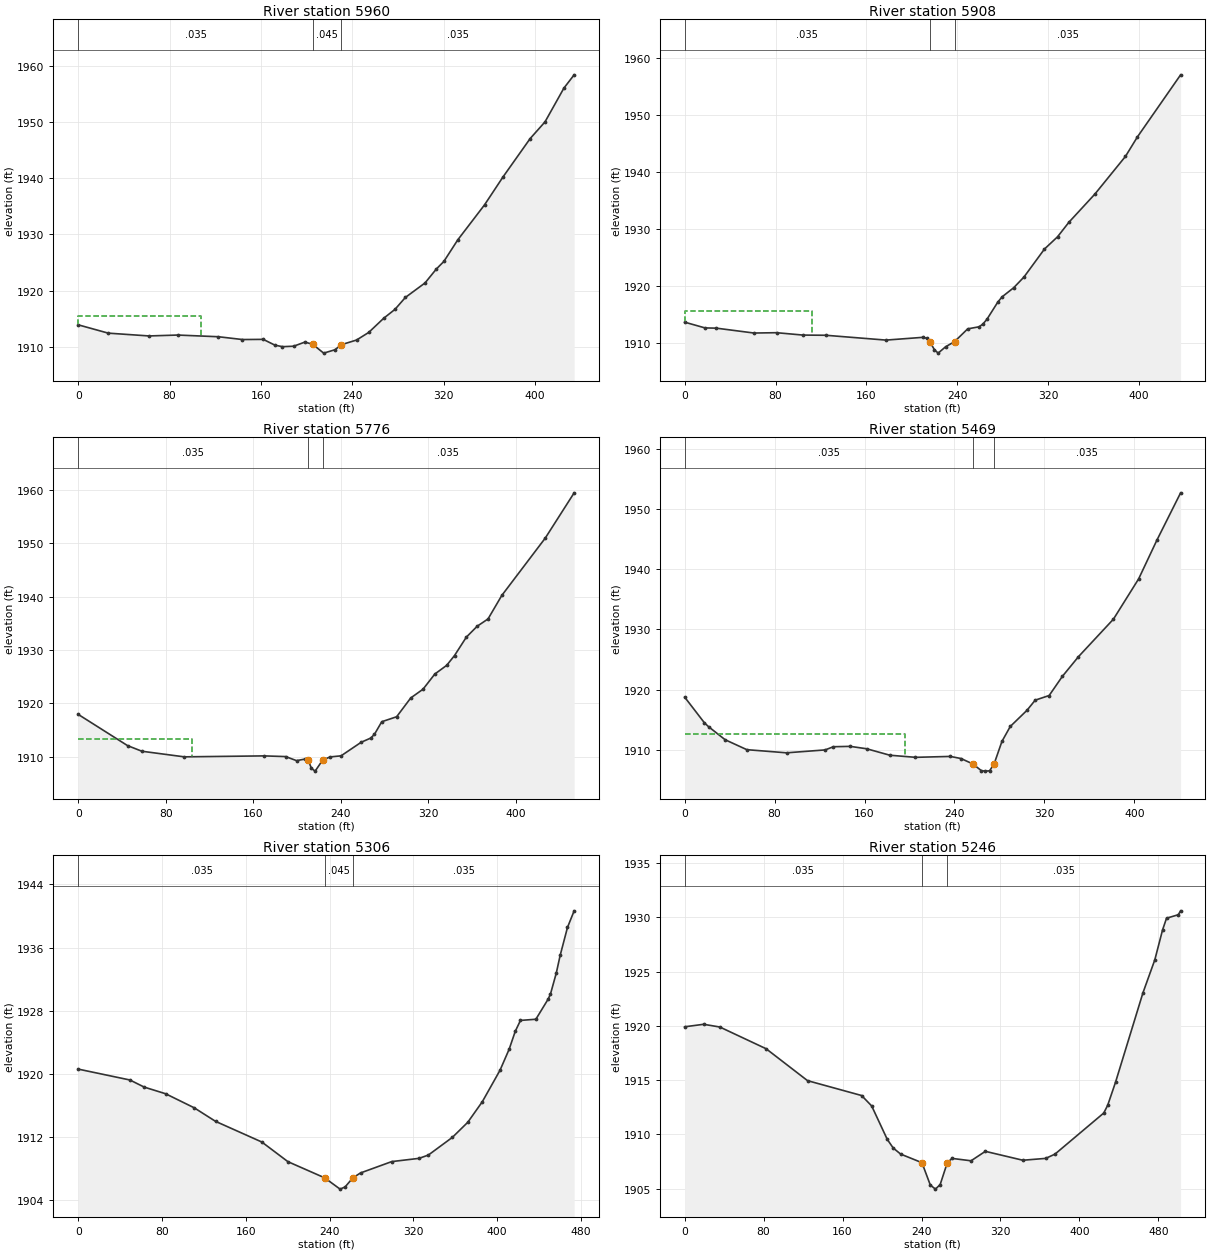
Type RM Length L Ch R = 1 ,5960    ,54.4,51.5,52.5
XS GIS Cut Line= 4
 2068610.1327316178196.9709951262068457.80643032178262.946717975
2068354.96192117178257.1253306652068190.02261405178269.738336504
#Sta/Elev= 30
       0 1913.89    26.3 1912.41      62 1911.91    87.1 1912.07   122.8 1911.77
   143.9 1911.27   162.1  1911.3   172.3 1910.27   178.9    1910   188.7 1910.08
   198.6 1910.82   205.5 1910.41     215 1908.85   224.9 1909.45  230.571910.355
   243.8 1911.18   254.5 1912.54   267.6 1915.06   277.5 1916.65   286.6 1918.77
   303.8 1921.35   313.7 1923.83   320.3 1925.18   332.5 1929.03   355.9 1935.25
   372.2 1940.26   395.9 1947.07   408.9 1950.04   425.5 1956.07434.4303 1958.42
#Mann= 3 ,-1 , 0
       0    .035       0   205.5    .045       0  230.57    .035       0
#XS Ineff= 3 ,-1
       0  107.45 1915.41  185.53  196.99    1910  238.54  267.91 1910.24
Permanent Ineff=
       F       F       F
Bank Sta=205.5,230.57
XS Rating Curve= 0 ,0
Exp/Cntr(USF)=0,0
Exp/Cntr=0.5,0.3

Type RM Length L Ch R = 1 ,5908    ,135,132.4,122.6
XS GIS Cut Line= 4
2068600.43041942178191.1496078152068428.69949377178217.345850711
2068281.22434857178213.4649258382068166.73706481178227.048162895
#Sta/Elev= 30
       0 1913.58    17.9 1912.57    27.8 1912.53      61 1911.67    80.9 1911.73
   104.2 1911.31   124.1 1911.28   177.2 1910.43     210 1910.92   213.3 1910.73
  215.761910.162   219.8 1908.75   223.1 1908.14   229.7 1909.26  237.531910.161
   249.1  1912.4   259.2 1912.77   262.5 1913.25     266 1914.07   275.6  1917.1
   279.4 1918.03   289.6 1919.63   298.6  1921.5   316.7 1926.43   328.2 1928.58
   338.1 1931.11     361 1936.07     388 1942.71   398.4  1946.1436.5339 1957.04
#Mann= 3 ,-1 , 0
       0    .035       0  215.76    .045       0  237.53    .035       0
#XS Ineff= 3 ,-1
       0  111.75 1915.53  189.83  209.17 1910.35  243.55  267.91 1910.35
Permanent Ineff=
       F       F       F
Bank Sta=215.76,237.53
XS Rating Curve= 0 ,0
Exp/Cntr(USF)=0,0
Exp/Cntr=0.5,0.3

Type RM Length L Ch R = 1 ,5776    ,296.8,307.3,298.6
XS GIS Cut Line= 4
2068552.29494447178089.8345897442068357.98251939178099.150938892
2068247.51723664178127.0999863352068115.75744155178186.990802284
#Sta/Elev= 30
       0 1917.96    45.1 1912.12    58.2 1911.07    96.9 1910.02   169.9  1910.2
   189.6 1910.07   199.5 1909.31   207.6 1909.62   210.3 1909.35   213.1 1907.88
   216.5 1907.35   223.3 1909.39     230    1910   240.2 1910.21   258.6 1912.75
   267.3 1913.53   270.7 1914.23   277.4 1916.59     291 1917.52   303.9 1921.04
   315.1 1922.67   325.9 1925.51   336.7 1927.13   343.9 1928.97   354.7 1932.41
   364.6 1934.45   374.5 1935.81   387.1 1940.21   426.8 1950.93453.2145  1959.4
#Mann= 3 ,-1 , 0
       0    .035       0   210.3    .045       0   223.3    .035       0
#XS Ineff= 2 , 0
          103.87 1913.29
Permanent Ineff=
       F       F
Bank Sta=210.3,223.3
XS Rating Curve= 0 ,0
Exp/Cntr(USF)=0,0
Exp/Cntr=0.3,0.1

Type RM Length L Ch R = 1 ,5469    ,163,162.9,163.7
XS GIS Cut Line= 4
2068411.21880023177844.9476978622068246.18632961177931.456654233
2068118.41925559177991.3474701832068029.24848517178061.885542301
#Sta/Elev= 30
       0 1918.75    17.5  1914.5    21.2 1913.85      36 1911.68    55.3 1910.03
    90.6 1909.51   124.9 1909.99   132.3 1910.52   147.2 1910.58   161.9 1910.18
   182.5 1909.11   205.3 1908.76   236.3 1908.91   245.8 1908.56  256.271907.668
   263.9 1906.55   267.2 1906.47   271.2 1906.52  275.241907.668   282.2  1911.4
   289.6 1913.88   304.4 1916.55   311.8 1918.25   324.2 1919.02     336 1922.21
   350.3 1925.47   381.4  1931.7   403.8 1938.38   420.1 1944.83441.1364 1952.66
#Mann= 3 ,-1 , 0
       0    .035       0  256.27    .045       0  275.24    .035       0
#XS Ineff= 2 , 0
          195.56 1912.71
Permanent Ineff=
       F       F
Bank Sta=256.27,275.24
XS Rating Curve= 0 ,0
Exp/Cntr(USF)=0,0
Exp/Cntr=0.5,0.3

Type RM Length L Ch R = 1 ,5306    ,60.6,60,59
XS GIS Cut Line= 4
2068315.39349471177754.4460204272068137.05195388177803.689580208
2068017.27032198177863.5803961572067902.81231817177967.391143803
#Sta/Elev= 30
       0 1920.59    49.4 1919.21      63 1918.31    83.4 1917.47   110.7 1915.69
   131.1 1913.97   175.3 1911.35   200.2 1908.86   235.3 1906.81     250 1905.38
   254.8 1905.66   262.2 1906.81   269.5 1907.43   299.3 1908.87   325.4 1909.28
   334.3  1909.7   357.2 1911.94   371.9 1913.85   385.8 1916.46   402.7 1920.45
   411.4 1923.11   417.3  1925.4   422.2 1926.76   436.9 1926.91   448.5 1929.43
   450.8 1930.08   456.4 1932.76   460.1    1935   467.1 1938.55 473.458 1940.65
#Mann= 3 ,-1 , 0
       0    .035       0   235.3    .045       0   262.2    .035       0
Bank Sta=235.3,262.2
XS Rating Curve= 0 ,0
Exp/Cntr(USF)=0,0
Exp/Cntr=0.5,0.3

Type RM Length L Ch R = 1 ,5246    ,106,100.6,96.8
XS GIS Cut Line= 4
2068288.77535429 177697.217018522068099.78655729177753.115113406
2067944.07043582177839.6240697782067872.20145669177944.765724444
#Sta/Elev= 30
       0 1919.91    19.2 1920.14    35.6 1919.89    82.5 1917.89   124.5 1914.95
   179.3 1913.58   189.5 1912.62   205.3 1909.54   211.3 1908.75   218.8 1908.19
  240.451907.395   248.9 1905.34   254.1 1904.96   258.9 1905.38  266.131907.395
   270.9 1907.79   290.2 1907.57   304.7 1908.44   342.7 1907.62   365.8 1907.79
   375.2 1908.18   424.7 1911.97   428.7 1912.69   436.6  1914.8   464.4 1923.04
   476.4 1926.07   484.3 1928.84   488.3 1929.91   500.2 1930.23502.5724 1930.59
#Mann= 3 ,-1 , 0
       0    .035       0  240.45    .045       0  266.13    .035       0
Bank Sta=240.45,266.13
XS Rating Curve= 0 ,0
Exp/Cntr(USF)=0,0
Exp/Cntr=0.5,0.3

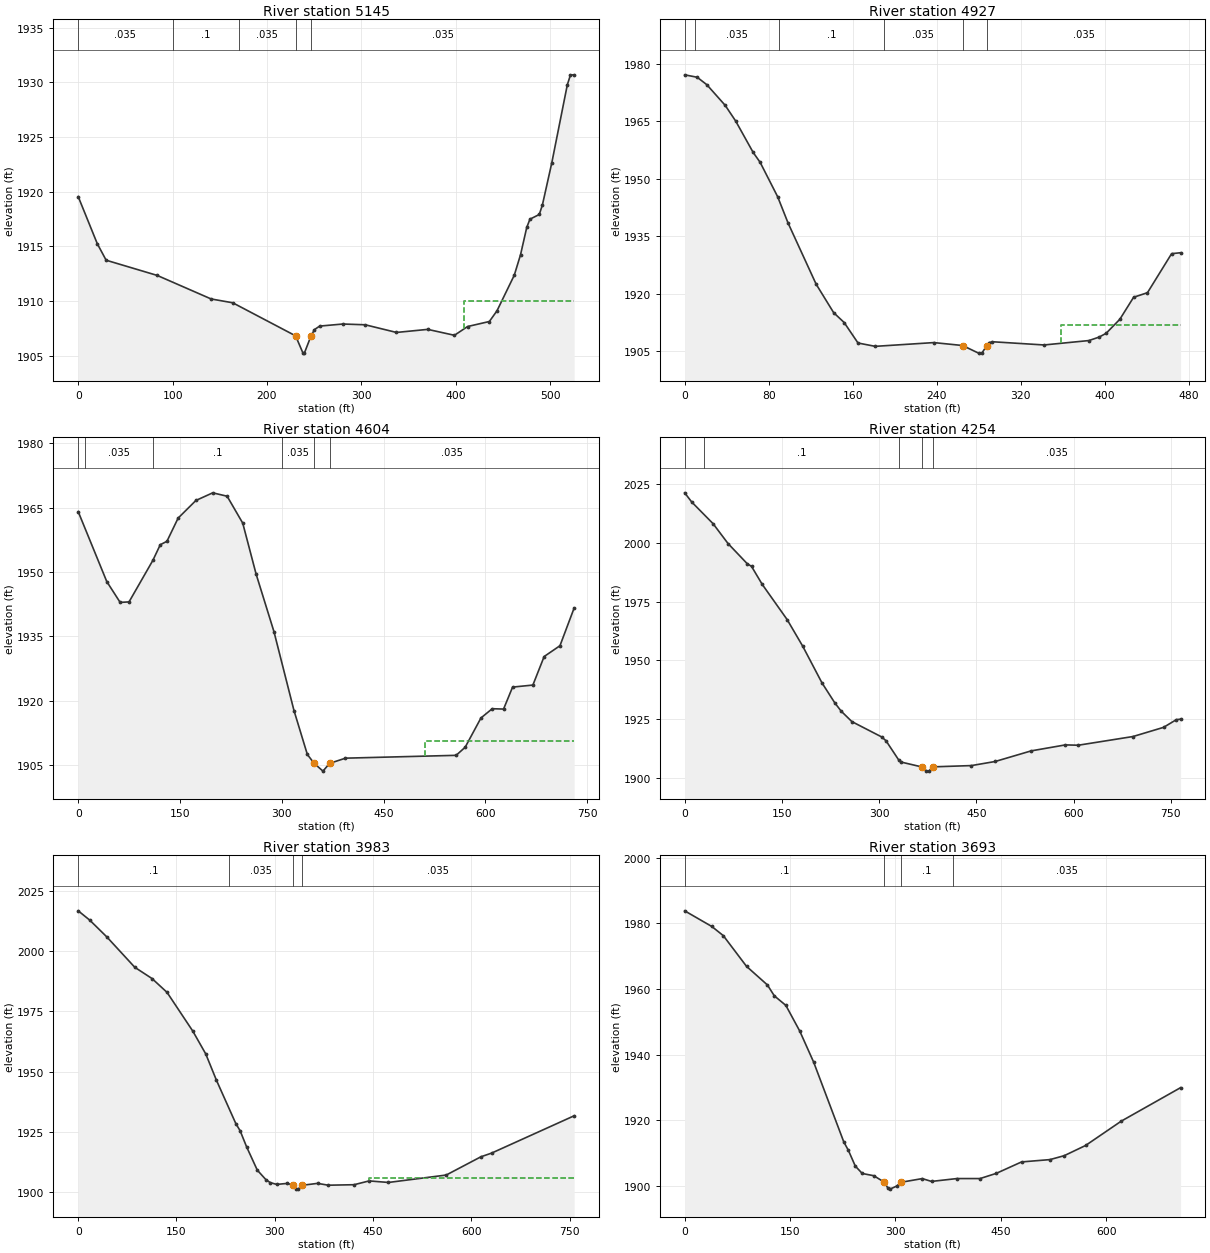
Type RM Length L Ch R = 1 ,5145    ,219.2,218.2,203.1
XS GIS Cut Line= 4
2068178.31007154177574.7735725792068017.27032198177671.929785119
2067864.21601456177819.6604644612067849.57603733177943.434817423
#Sta/Elev= 30
       0 1919.55    20.2 1915.25    29.6 1913.74    83.7 1912.35   140.8  1910.2
   163.7 1909.85   230.3 1906.83     238 1905.28   239.6 1905.25   246.6 1906.81
   250.3  1907.4   255.8 1907.72   280.5 1907.91   304.1 1907.84   337.2 1907.14
   370.3 1907.42   398.6 1906.88   412.5 1907.68   435.6 1908.14   443.7 1909.12
     462 1912.37   468.6 1914.23   475.2 1916.73   478.6 1917.49   488.5 1917.92
   491.8 1918.79   501.7 1922.62   518.2 1929.77   521.5 1930.66 525.435 1930.68
#Mann= 5 ,-1 , 0
       0    .035       0     100      .1       0     170    .035       0
   230.3    .045       0   246.6    .035       0
#XS Ineff= 2 , 0
                          408.31            1910
Permanent Ineff=
       F       F
Bank Sta=230.3,246.6
XS Rating Curve= 0 ,0
Exp/Cntr(USF)=0,0
Exp/Cntr=0.3,0.1

Type RM Length L Ch R = 1 ,4927    ,315.3,323.4,314.9
XS GIS Cut Line= 4
2067799.00157052177481.6100811022067826.95061797177638.657109592
2067826.95061797177803.6895802082067832.27424605 177951.42025955
#Sta/Elev= 30
       0 1977.15    11.9 1976.52    21.1 1974.57    38.6 1969.18    48.6 1965.08
    65.2 1956.91    71.9  1954.3    88.6 1945.31    98.5 1938.46   125.2 1922.52
   141.9 1915.08   151.9 1912.51   165.1 1907.16   181.5 1906.29   237.3 1907.27
   264.7 1906.51   279.9 1904.52   283.2 1904.59  287.721906.447   289.8 1907.24
   293.1 1907.49   342.3 1906.65     385  1907.8   394.8 1908.71   401.4 1909.69
   414.5 1913.36   427.6  1919.1   440.8 1920.29   463.8 1930.48472.3737 1930.72
#Mann= 6 ,-1 , 0
       0      .1       0      10    .035       0      90      .1       0
  189.51    .035       0   264.7    .045       0  287.72    .035       0
#XS Ineff= 2 , 0
                          358.88         1911.92
Permanent Ineff=
       F       F
Bank Sta=264.7,287.72
XS Rating Curve= 0 ,0
Exp/Cntr(USF)=0,0
Exp/Cntr=0.3,0.1

Type RM Length L Ch R = 1 ,4604    ,344.8,349.3,347.5
XS GIS Cut Line= 3
      2067604.54      177362.724     2067620.328        177725.8
     2067680.714      178088.095
#Sta/Elev= 30
       0 1964.04    42.1 1947.75    61.8  1942.9    74.9 1943.02     110  1952.7
   120.9 1956.34   130.7 1957.13   147.2 1962.54   173.4 1966.65   198.2 1968.43
   219.4 1967.64   242.4 1961.37   262.1  1949.5   288.4 1936.09   317.9 1917.71
   337.6 1907.47   347.5 1905.43   360.6 1903.59   370.3 1905.39   393.8 1906.61
   556.8 1907.27   570.1 1909.15   593.4 1915.98     610 1918.13   626.7 1918.05
     640 1923.17   669.9 1923.64   686.5 1930.29   709.8 1932.81   730.7  1941.6
#Mann= 6 ,-1 , 0
       0      .1       0      10    .035       0     110      .1       0
     300    .035       0   347.5    .045       0   370.3    .035       0
#XS Ineff= 2 , 0
                          511.17         1910.71
Permanent Ineff=
       F       F
Bank Sta=347.5,370.3
XS Rating Curve= 0 ,0
Exp/Cntr=0.3,0.1

Type RM Length L Ch R = 1 ,4254    ,267.1,271.1,270.7
XS GIS Cut Line= 2
     2067295.045      177338.085     2067361.017      178100.238
#Sta/Elev= 30
       0 2021.35    10.9 2017.43    43.9 2008.19    66.9 1999.76    96.4 1991.21
   103.1 1990.05   119.6 1982.39     158 1967.42   182.2 1956.02   211.8 1940.45
   231.6 1931.94   241.4 1928.43   257.9 1923.98     304 1917.43   310.6 1915.81
   330.4 1907.54   333.7 1906.77   366.6 1904.63   372.2  1903.1   376.5  1902.9
   383.1 1904.72   442.3 1905.26   478.9    1907   534.5 1911.52   587.4 1914.07
     607 1913.92   691.6 1917.63   738.7 1921.53   758.5 1924.82     765 1925.01
#Mann= 5 ,-1 , 0
       0    .035       0      30      .1       0     330    .035       0
   366.6    .045       0   383.1    .035       0
Bank Sta=366.6,383.1
XS Rating Curve= 0 ,0
Exp/Cntr=0.3,0.1

Type RM Length L Ch R = 1 ,3983    ,287.3,290.4,285.1
XS GIS Cut Line= 2
     2067081.503      177338.085     2067065.878      178095.029
#Sta/Elev= 30
       0 2016.73    17.5 2012.89    43.7 2005.89    86.4 1993.28   112.6 1988.63
   135.6 1982.88     175 1966.76   194.7 1957.32   211.1 1946.34   240.6 1928.41
   247.2 1925.41     257 1918.79   273.4 1909.06   286.5 1905.14   293.1 1903.91
     303 1903.15   319.4 1903.57  328.591902.787   332.5 1901.36   335.8 1901.19
  342.141902.785   365.3 1903.58   381.7 1902.82   421.1 1903.02   444.1  1904.6
   473.6 1903.96   561.8 1907.04   614.7 1914.61   631.1 1916.15   757.1 1931.64
#Mann= 4 ,-1 , 0
       0      .1       0     230    .035       0  328.59    .045       0
  342.14    .035       0
#XS Ineff= 2 , 0
                          444.41         1905.71
Permanent Ineff=
       F       F
Bank Sta=328.59,342.14
XS Rating Curve= 0 ,0
Exp/Cntr=0.3,0.1

Type RM Length L Ch R = 1 ,3693    ,232.5,231,217.9
XS GIS Cut Line= 4
2066877.81096069177389.3346530122066898.09608523177600.299948233
2066914.32418486177876.1776419842066967.06550867178087.142937204
#Sta/Elev= 30
       0 1983.83    38.6 1979.06      55 1976.26      88 1966.91   117.7 1961.24
   127.6 1957.91     144    1955   163.8 1947.16   183.6 1937.68   226.4  1913.4
     233  1910.8   242.8 1906.02   252.7 1903.76   269.1 1903.08  284.371901.069
   288.8 1899.44   292.1 1898.99     302 1899.94  307.691901.069   338.1  1902.2
   351.3 1901.34   387.4 1902.21   420.3 1902.21   443.3 1903.78   479.4 1907.28
   519.8 1907.99   540.1 1909.18   570.5 1912.29   621.2  1919.7   705.8 1929.93
#Mann= 4 ,-1 , 0
       0      .1       0  284.37    .045       0  307.69      .1       0
  381.94    .035       0
Bank Sta=284.37,307.69
XS Rating Curve= 0 ,0
Exp/Cntr(USF)=0,0
Exp/Cntr=0.3,0.1

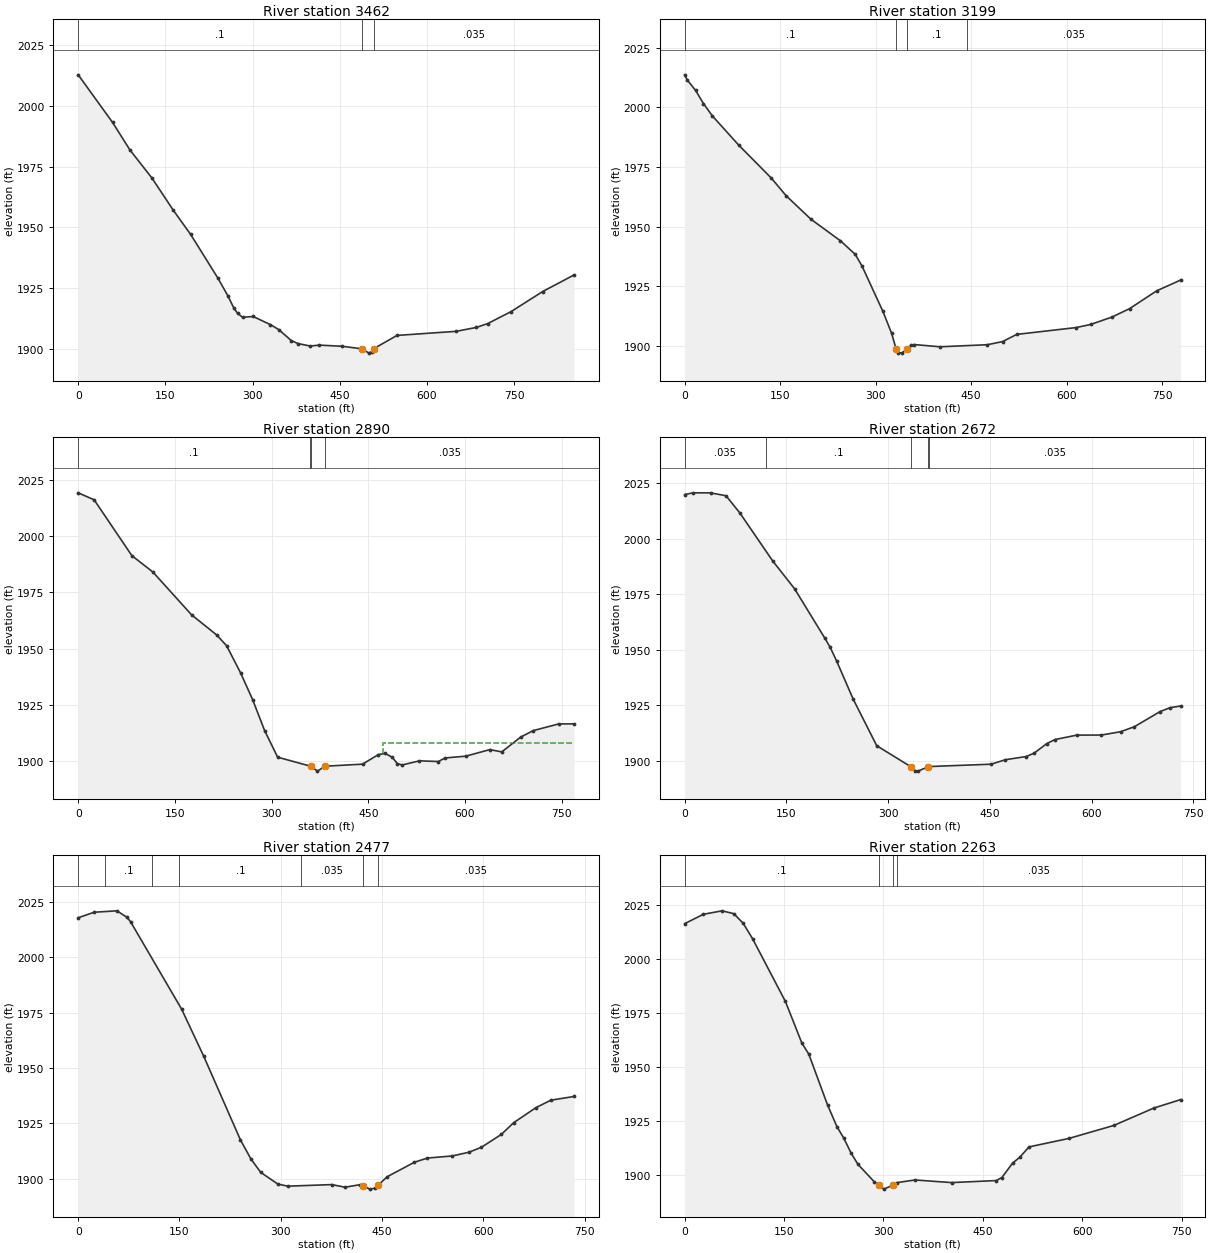
Type RM Length L Ch R = 1 ,3462    ,266.1,263.2,255
XS GIS Cut Line= 3
     2066440.878      177449.196     2066694.351      177586.349
     2066937.406      178096.765
#Sta/Elev= 30
       0 2012.77    59.1  1993.2    88.9  1981.9   126.6 1970.41   163.5 1957.12
   193.4 1947.16   240.4 1929.15   257.3 1921.99     268 1916.77   274.2 1914.71
   282.9 1913.02   301.1 1913.38   330.8 1910.01   345.1 1907.99   366.9 1903.42
   378.8  1902.2   399.5 1901.21   414.7  1901.6   454.1 1901.12  487.921900.085
   500.5  1898.3     505 1898.87  508.251900.085   548.6 1905.58   650.3 1907.26
   685.1 1908.86   704.8 1910.46   744.8 1915.36   799.3 1923.63   853.5 1930.48
#Mann= 3 ,-1 , 0
       0      .1       0  487.92    .045       0  508.25    .035       0
Bank Sta=487.92,508.25
XS Rating Curve= 0 ,0
Exp/Cntr=0.3,0.1

Type RM Length L Ch R = 1 ,3199    ,300.5,309.1,308.4
XS GIS Cut Line= 3
     2066279.598      177577.522      2066554.17      177799.554
     2066855.281      178100.636
#Sta/Elev= 30
       0 2013.63     4.2 2011.39    17.1 2007.11    29.5 2001.58    43.5 1996.39
    84.8 1984.17   136.1  1970.3   159.4 1962.89   198.3 1953.06   244.7    1944
   267.9 1938.31   278.5 1933.43   311.1 1914.53   325.1 1905.15  331.971898.678
   335.7 1897.14   340.9 1896.89  349.721898.676   355.4 1900.19   360.8 1900.48
   400.9 1899.55   475.2 1900.41   499.2 1901.73   521.6 1904.75   614.4  1907.6
   637.6 1908.91   670.9    1912   698.7 1915.54   741.3 1923.02   778.9 1927.55
#Mann= 4 ,-1 , 0
       0      .1       0  331.97    .045       0  349.72      .1       0
  443.11    .035       0
Bank Sta=331.97,349.72
XS Rating Curve= 0 ,0
Exp/Cntr=0.3,0.1

Type RM Length L Ch R = 1 ,2890    ,214.8,218,212.9
XS GIS Cut Line= 3
     2066173.056      177673.561     2066405.436      177979.172
     2066663.177      178265.787
#Sta/Elev= 30
       0  2019.1    24.7    2016    83.2 1991.25   115.7 1984.01     176 1964.95
   214.6 1956.11   230.2 1951.28   251.8  1939.3   270.5 1927.42   289.2 1913.65
   309.4 1901.84  360.55 1897.84   371.2 1895.66  382.781897.841   441.1 1898.75
   465.6 1902.99   476.2  1903.5   487.4 1901.77     495    1899   502.7  1898.4
   529.4 1900.23   558.8 1899.92   568.9 1901.49   601.3  1902.3   638.5  1905.2
   657.1 1904.19   686.4 1910.75   705.7 1913.61   745.3 1916.59   769.4 1916.63
#Mann= 4 ,-1 , 0
       0      .1       0     360    .035       0  360.55    .045       0
  382.78    .035       0
#XS Ineff= 2 , 0
                          472.24         1908.14
Permanent Ineff=
       F       F
Bank Sta=360.55,382.78
XS Rating Curve= 0 ,0
Exp/Cntr=0.3,0.1

Type RM Length L Ch R = 1 ,2672    ,190.7,194.1,193.8
XS GIS Cut Line= 2
     2066062.406       177768.64     2066489.489       178362.39
#Sta/Elev= 30
       0 2019.78    12.4 2020.56    38.3 2020.54      61 2019.24    81.2 2011.58
   129.7 1989.98     162 1977.45   206.5 1955.31   214.6  1951.1     224    1945
   248.3 1927.94   283.2 1906.86  333.951897.334   339.2 1895.69   343.9 1895.43
  358.841897.335     360 1897.48     452 1898.55   473.1 1900.57   503.7 1901.99
   515.5 1903.53   533.8 1907.76   546.1 1909.63   578.3 1911.62   614.6 1911.66
   642.9 1913.15   663.1 1915.38   701.2 1922.22   715.7 1923.94   731.4 1924.71
#Mann= 5 ,-1 , 0
       0    .035       0     120      .1       0  333.95    .045       0
  358.84      .1       0     360    .035       0
Bank Sta=333.95,358.84
XS Rating Curve= 0 ,0
Exp/Cntr=0.3,0.1

Type RM Length L Ch R = 1 ,2477    ,210.7,214.1,214.2
XS GIS Cut Line= 2
     2065980.809      177825.932      2066310.67      178482.182
#Sta/Elev= 30
       0 2017.85    23.7 2020.34    57.4 2020.97    72.1 2018.05    77.5 2016.07
   153.2 1976.52   185.9 1955.26   240.3 1917.45   255.8 1908.85   270.3  1902.8
     296 1897.46   310.7 1896.57   375.6 1897.28   395.2 1896.09   417.1 1897.22
     422 1896.78   431.8 1895.23   439.3  1895.6     444 1896.97   457.6 1900.83
     498 1907.39   517.3 1909.27     554 1910.22   578.8 1911.91   597.2 1914.15
   626.5 1919.92   644.9 1925.23   677.9 1932.05     700 1935.41   734.5  1937.1
#Mann= 7 ,-1 , 0
       0    .035       0      40      .1       0     110    .035       0
     150      .1       0     330    .035       0     422    .045       0
     444    .035       0
Bank Sta=422,444
XS Rating Curve= 0 ,0
Exp/Cntr=0.3,0.1

Type RM Length L Ch R = 1 ,2263    ,234.2,237.8,236.5
XS GIS Cut Line= 2
      2065873.17      177864.127     2066152.684      178558.571
#Sta/Elev= 30
       0 2016.15    28.2 2020.48    56.5 2022.08    74.2 2020.76    88.4 2016.28
   102.5 2009.16     152 1980.18   176.8 1960.96   187.4 1955.74   215.7 1932.22
   229.8 1922.25   240.4 1916.76     251  1910.1   261.6 1904.76   286.4 1896.65
  293.941895.191   300.5 1893.31  314.851895.191   319.9  1896.3   347.6 1897.55
   403.1 1896.33   470.3 1897.28   478.8 1898.69   495.1 1905.38   505.7 1908.02
   519.8 1912.85   579.9 1916.76   647.7 1922.77   708.2 1930.83   748.6 1934.73
#Mann= 4 ,-1 , 0
       0      .1       0  293.94    .045       0  314.85      .1       0
     320    .035       0
Bank Sta=293.94,314.85
XS Rating Curve= 0 ,0
Exp/Cntr=0.3,0.1

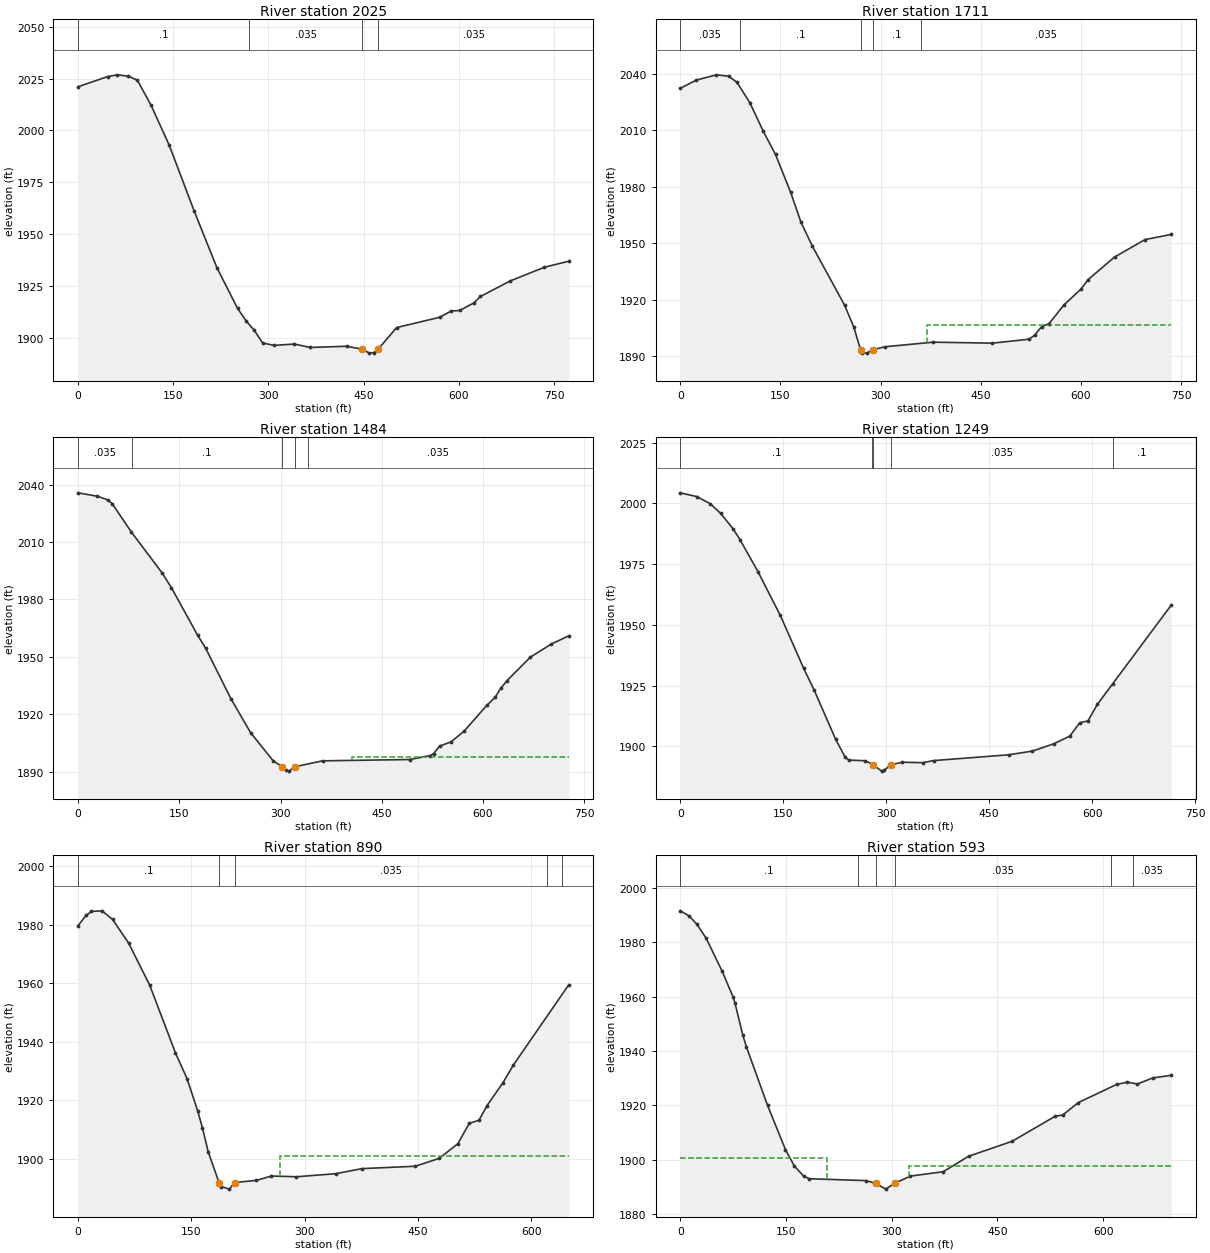
Type RM Length L Ch R = 1 ,2025    ,307.7,314.4,309.7
XS GIS Cut Line= 2
     2065701.295      177912.738     2066011.191      178621.071
#Sta/Elev= 30
       0 2021.05    47.1 2025.99    61.5  2026.8    79.4 2026.17    93.7 2024.14
   115.2 2012.08   143.8 1992.82   182.9 1961.22     219 1933.66   251.3 1914.18
   265.1 1907.98   277.6 1903.61   290.7  1897.5   308.6 1896.27   340.8 1896.92
   365.9 1895.27   423.2 1895.85  448.041894.415     459 1892.54   466.1 1892.82
  472.721894.414   501.9 1904.87     570 1909.85   587.9 1912.86   601.5 1913.12
   623.9 1916.85   633.8 1919.86     681 1927.39   734.7 1933.98   773.2 1936.89
#Mann= 4 ,-1 , 0
       0      .1       0     270    .035       0  448.04    .045       0
  472.72    .035       0
Bank Sta=448.04,472.72
XS Rating Curve= 0 ,0
Exp/Cntr=0.3,0.1

Type RM Length L Ch R = 1 ,1711    ,229.5,227.2,222.6
XS GIS Cut Line= 2
      2065498.17      178032.529     2065834.108      178686.175
#Sta/Elev= 30
       0 2032.39      24 2036.74    54.1 2039.56    72.5  2038.8    84.9 2035.62
   104.4 2024.59   124.1 2009.67   142.6 1997.24   165.3 1977.06   180.7 1961.21
   197.9 1948.38   245.9 1917.15   259.7 1905.56  270.011893.321   271.7 1891.83
   279.1 1891.57  287.991893.318   306.6 1894.97   378.7 1897.39   467.4 1896.88
   522.5 1898.99   530.8 1901.22     541 1905.66     552 1907.23   574.6 1917.27
     600 1925.67   610.7 1930.69   650.1 1942.64   695.9 1951.97   734.9 1954.68
#Mann= 5 ,-1 , 0
       0    .035       0      90      .1       0  270.01    .045       0
  287.99      .1       0     360    .035       0
#XS Ineff= 2 , 0
                          369.05         1906.67
Permanent Ineff=
       F       F
Bank Sta=270.01,287.99
XS Rating Curve= 0 ,0
Exp/Cntr=0.3,0.1

Type RM Length L Ch R = 1 ,1484    ,231.1,234.8,237.5
XS GIS Cut Line= 2
     2065253.378      178196.592     2065732.545      178743.467
#Sta/Elev= 30
       0 2035.72    28.9 2033.92    43.8 2032.08    50.8 2030.05    78.6 2015.49
     125 1993.72   138.4 1986.17   177.3  1961.3   189.3 1954.43   226.5 1928.17
   255.8 1910.38   289.3 1895.66  302.451892.681   307.6 1890.72   312.6 1890.33
  322.161892.681   362.4 1895.71   491.6 1896.39   521.7 1898.47   526.7 1899.46
   535.8 1903.43   552.4 1905.58   571.5 1911.04   605.5 1924.66   617.9 1928.88
   626.2  1933.6   635.7 1937.66   670.2  1949.9   700.7 1956.64   727.1 1961.05
#Mann= 5 ,-1 , 0
       0    .035       0      80      .1       0  302.45    .045       0
  322.16      .1       0     340    .035       0
#XS Ineff= 2 , 0
                          405.93         1897.47
Permanent Ineff=
       F       F
Bank Sta=302.45,322.16
XS Rating Curve= 0 ,0
Exp/Cntr=0.3,0.1

Type RM Length L Ch R = 1 ,1249    ,368.8,359.1,347.4
XS GIS Cut Line= 2
     2065125.774      178308.571     2065482.545      178928.363
#Sta/Elev= 30
       0  2004.3    24.5 2002.72      44 1999.76    58.7 1995.89    76.9 1989.51
      87 1985.06   113.4 1971.76   145.8 1953.83   179.9 1932.01   195.1 1923.09
   226.3 1902.93   240.4 1895.43   245.5 1894.32   269.6 1894.04  281.051892.375
   293.4 1889.77   297.2 1890.11  306.661892.377   323.7 1893.43   353.7 1893.25
   369.1 1894.11   478.6 1896.49     513 1898.02   543.8 1900.98   567.5 1904.18
   581.9 1909.63   593.9 1910.45   607.6 1917.23     630 1925.73   715.1 1958.04
#Mann= 5 ,-1 , 0
       0      .1       0     280    .035       0  281.05    .045       0
  306.66    .035       0     630      .1       0
Bank Sta=281.05,306.66
XS Rating Curve= 0 ,0
Exp/Cntr=0.3,0.1

Type RM Length L Ch R = 1 ,890     ,285.9,296.7,306.6
XS GIS Cut Line= 2
     2064865.358      178714.821     2065472.128      178946.592
#Sta/Elev= 30
       0 1979.65    10.8  1983.2    17.8 1984.55    31.8 1984.76    45.9  1981.8
    66.9 1973.79      95 1959.31     129 1936.18   144.3 1927.41   158.3 1916.44
   164.6 1910.67   172.3 1902.39  186.611891.873   189.9 1890.48   200.4 1889.61
  207.211891.871   236.2 1892.59     256  1894.1   289.1 1893.84   340.9 1894.88
     376 1896.63   446.2 1897.43   477.9 1900.12   502.5  1905.1   517.8 1912.11
   530.6 1913.16   541.1 1918.13   562.1  1925.9   576.2 1932.09   649.5 1959.51
#Mann= 5 ,-1 , 0
       0      .1       0  186.61    .045       0  207.21    .035       0
     620      .1       0     640    .035       0
#XS Ineff= 2 , 0
                          267.77         1900.94
Permanent Ineff=
       F       F
Bank Sta=186.61,207.21
XS Rating Curve= 0 ,0
Exp/Cntr=0.3,0.1

Type RM Length L Ch R = 1 ,593     ,153.1,157.9,159.4
XS GIS Cut Line= 4
2064845.24148173 178851.89213238 2064930.4390048178953.317755082
2065068.37785168179123.7128012222065297.59975899179381.333882886
#Sta/Elev= 30
       0 1991.52    12.5 1989.65    23.5 1986.62    36.7 1981.48    59.6 1969.24
    74.8 1959.98    77.5 1957.79    88.7 1945.86    93.9 1941.48   123.9    1920
   149.3 1903.74     162 1897.67     175 1894.04   183.1 1893.04   263.6 1892.35
  277.161891.334   291.6 1889.22  304.161891.335   326.6 1894.01   373.2 1895.63
     409 1901.29   470.8 1906.79     532 1916.01   542.8 1916.48   564.8 1921.03
   619.1 1927.71   633.9 1928.55   648.7 1927.87   670.6 1930.11   696.5 1931.05
#Mann= 6 ,-1 , 0
       0      .1       0  252.46    .035       0  277.16    .045       0
  304.16    .035       0  611.69      .1       0  641.69    .035       0
#XS Ineff= 2 , 0
          207.59 1900.71  323.93         1897.65
Permanent Ineff=
       F       F
Bank Sta=277.16,304.16
XS Rating Curve= 0 ,0
Exp/Cntr(USF)=0,0
Exp/Cntr=0.5,0.3