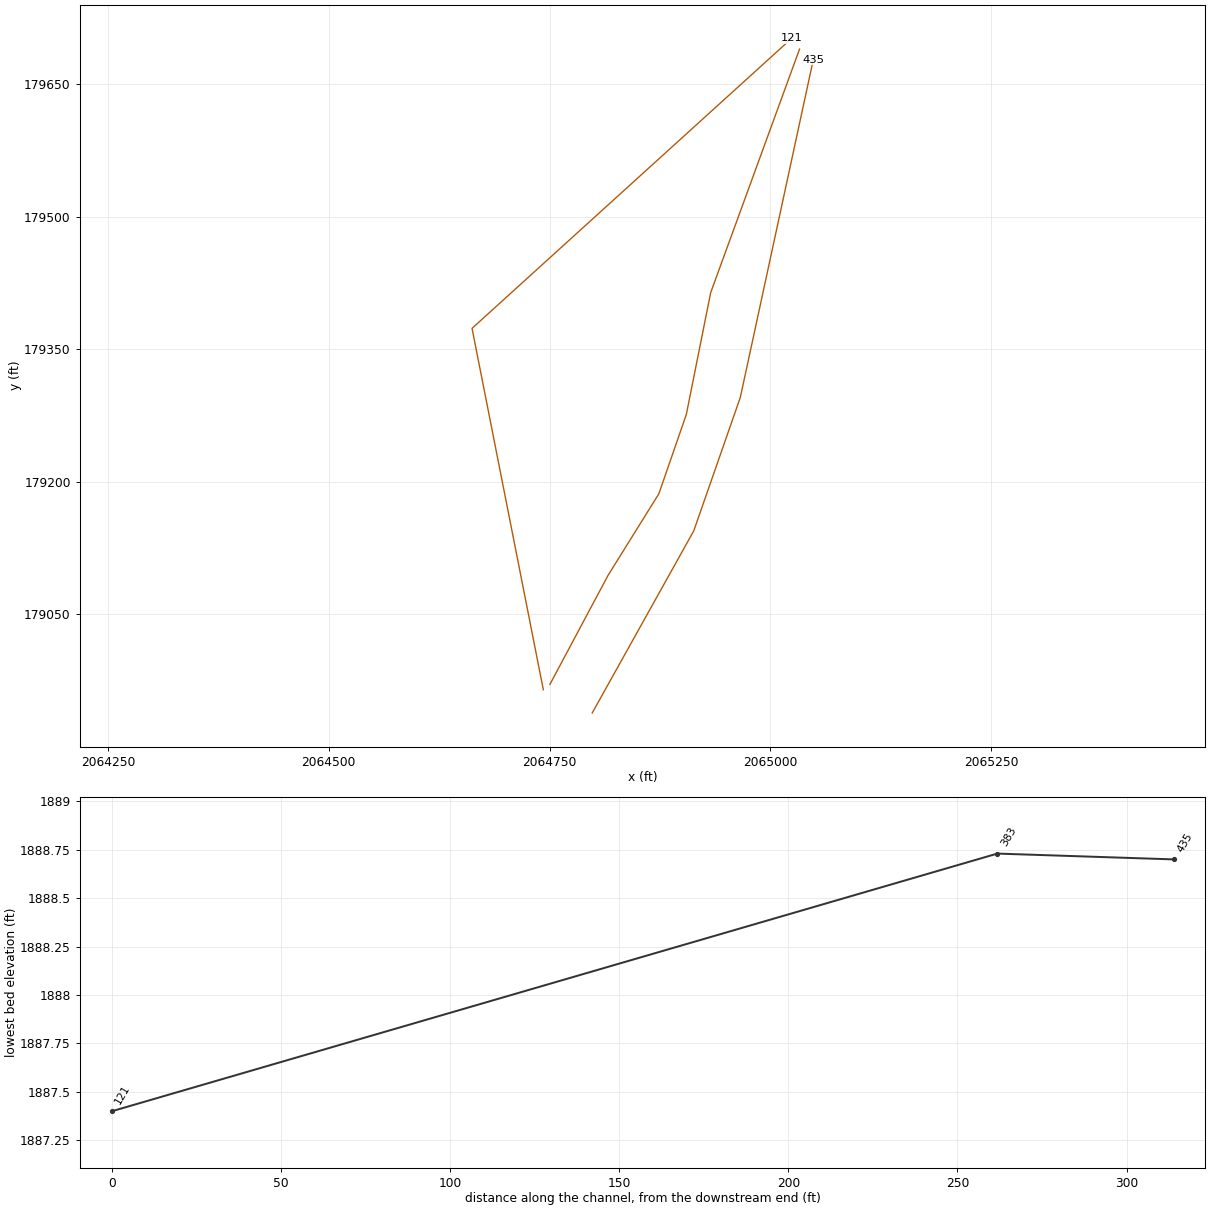
HEC-RAS study LICKRN.prj: LICKRN

--- LICKRN.g01 (geometry) --- (continued)

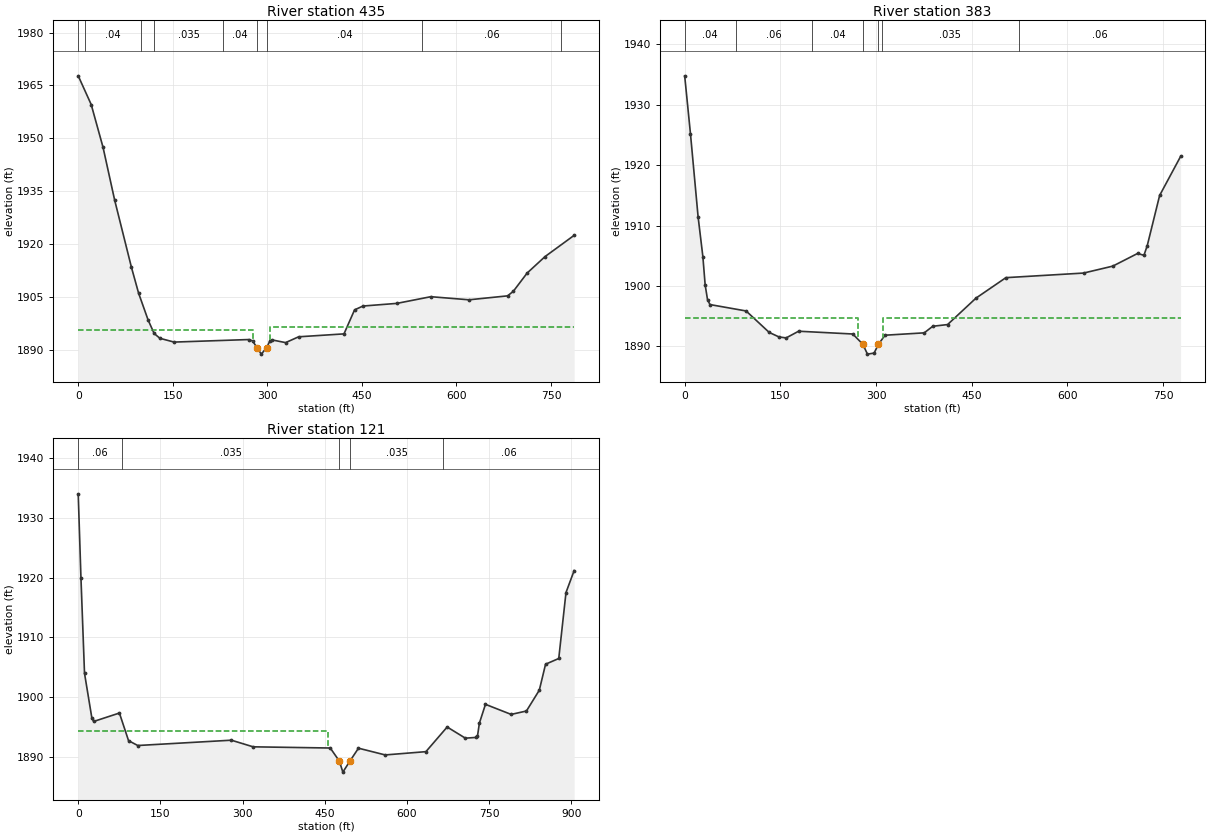
Type RM Length L Ch R = 1 ,435     ,52.4,52.1,54.8
XS GIS Cut Line= 4
2064798.30914819178938.5650736982064913.29951481179144.589480565
2064966.00343285179295.5143367572065048.65275886179677.617742515
#Sta/Elev= 30
       0 1967.74    20.6 1959.59    39.4 1947.42    57.8 1932.45    84.5 1913.31
    95.8 1906.01   110.9 1898.38   120.5 1894.56   129.6 1893.19   152.1 1892.12
   270.3 1892.84   276.6 1892.48  283.421890.564   290.5  1888.7  298.861890.564
   304.4 1892.55   307.9 1892.72     329 1891.97   349.6 1893.62   421.6 1894.45
   438.4 1901.28   451.8 1902.36   505.5 1903.11   559.3 1905.01   619.9 1904.13
   681.1 1905.25   690.2 1906.54   712.1 1911.72   740.5  1916.4   786.7 1922.44
#Mann= 9 ,-1 , 0
       0      .1       0      10     .04       0     100      .1       0
     120    .035       0     230     .04       0  283.42    .045       0
  298.86     .04       0   545.8     .06       0   765.8    .035       0
#XS Ineff= 2 , 0
          277.36 1895.69  304.87         1896.27
Permanent Ineff=
       F       F
Bank Sta=283.42,298.86
XS Rating Curve= 0 ,0
Exp/Cntr(USF)=0,0
Exp/Cntr=0.5,0.3

Type RM Length L Ch R = 1 ,383     ,268.8,261.8,251.9
XS GIS Cut Line= 6
2064750.39649543178970.9061143112064816.27639297179094.281195167
2064873.77157628179186.5130517292064904.91480058179276.349275653
2064932.46457591179414.0981523372065033.08114671179689.595905705
#Sta/Elev= 30
       0 1934.77     9.1 1925.16      21 1911.48    28.5 1904.87    32.1 1900.18
    35.8 1897.75    39.6 1896.93    96.3 1895.87   132.5 1892.32   147.7 1891.58
     159 1891.41   178.6 1892.52   263.5 1892.06  279.241890.366   286.5 1888.73
   296.9  1888.9  303.761890.367   314.1 1891.86   375.5 1892.25   388.9 1893.34
   412.1 1893.62   456.7    1898   503.5 1901.38   625.2 1902.14   671.1 1903.29
   709.9 1905.38   719.9 1905.08     725 1906.64   744.5 1914.98   777.4 1921.44
#Mann= 7 ,-1 , 0
       0     .04       0      80     .06       0  199.86     .04       0
  279.24    .045       0  303.76     .04       0  308.55    .035       0
  524.11     .06       0
#XS Ineff= 2 , 0
          271.63 1894.71   310.2         1894.78
Permanent Ineff=
       F       F
Bank Sta=279.24,303.76
XS Rating Curve= 0 ,0
Exp/Cntr(USF)=0,0
Exp/Cntr=0.5,0.3

Type RM Length L Ch R = 1 ,121     ,117.7,121.5,125.3
XS GIS Cut Line= 3
     2064742.962      178964.821     2064662.233      179373.675
     2065024.212        179701.8
#Sta/Elev= 30
       0 1934.03       5 1919.95    11.5 1903.96      25 1896.42    28.3 1895.89
    75.2  1897.3    91.9 1892.67   108.7 1891.86   279.6 1892.75   319.3 1891.64
   460.1 1891.44  476.691889.249   483.1  1887.4  495.951889.247   511.6 1891.41
   560.4 1890.28   634.7 1890.83   673.5 1894.96   706.7 1893.09   725.3 1893.21
   728.8 1893.41   732.3  1895.6   743.4 1898.76   790.3 1897.07   818.2 1897.64
   841.7 1901.13   853.1 1905.48   877.2 1906.44   890.4 1917.49   905.3 1921.17
#Mann= 5 ,-1 , 0
       0     .06       0      80    .035       0  476.69    .045       0
  495.95    .035       0  666.75     .06       0
#XS Ineff= 2 , 0
          455.59 1894.35
Permanent Ineff=
       F       F
Bank Sta=476.69,495.95
XS Rating Curve= 0 ,0
Exp/Cntr=0.3,0.1
LCMann Table=0

Chan Stop Cuts=-1
Use User Specified Reach Order=0
Composite Channel Slope=5